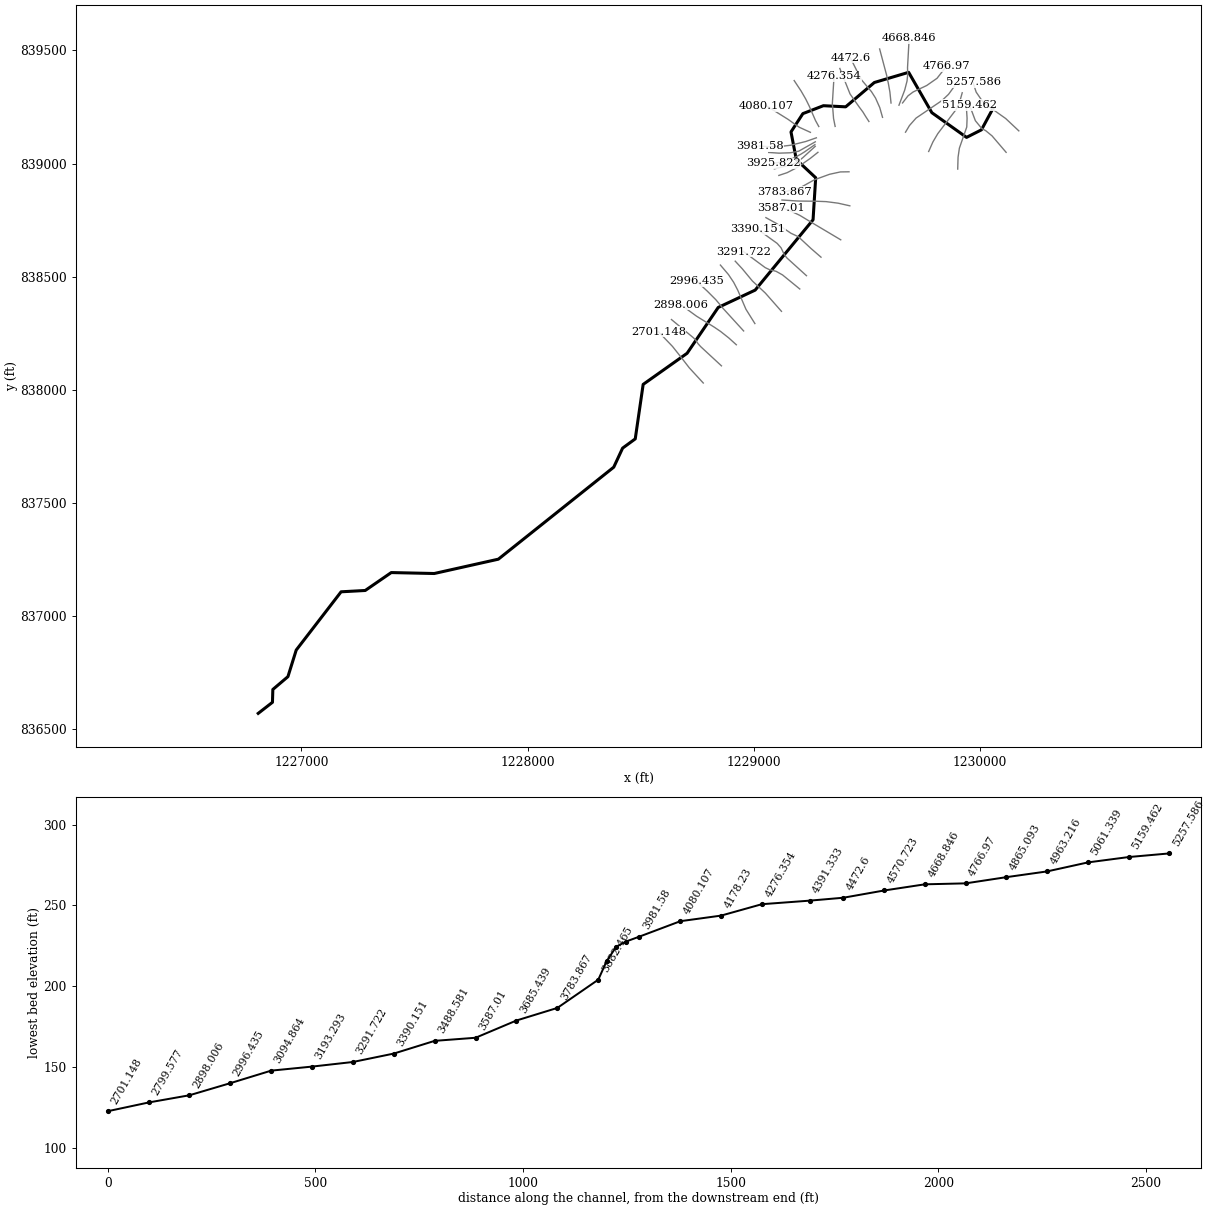
--- 5_ras.prj (project) ---

Proj Title=5
Current Plan=p01
Default Exp/Contr=0.3,0.1
English Units
Geom File=g01
Flow File=f01
Plan File=p01
Y Axis Title=Elevation
X Axis Title(PF)=Main Channel Distance
X Axis Title(XS)=Station
BEGIN DESCRIPTION:
RFD model 5 exported to HEC-RAS
END DESCRIPTION:

--- 5_ras.p01 (plan) ---

Plan Title=Plan 01
Program Version=4.10
Short Identifier=Plan 01
Geom File=g01
Flow File=f01
Subcritical Flow
Calc Critical at every XS
Secant Critical Depth

--- 5_ras.f01 (steady flow) ---

Flow Title=Flow 01
Program Version=5.01
Number of Profiles= 5
Profile Names=10yr,25yr,50yr,100yr,500yr
River Rch & RM=5,44,5257.586
  454.33  831.45 1215.51 1697.03 3256.79
River Rch & RM=5,44,5061.339
  508.72   933.3 1367.66 1914.35 3699.17
River Rch & RM=5,44,4963.216
  511.11  937.78 1374.35 1923.93 3718.73
River Rch & RM=5,44,4865.093
  513.49  942.25 1381.04  1933.5 3738.29
River Rch & RM=5,44, 4766.97
  536.15  984.76 1444.65 2024.53 3924.58
River Rch & RM=5,44,4570.723
  539.13  990.35 1453.02 2036.52 3949.15
River Rch & RM=5,44,  4472.6
   542.7  997.06 1463.07 2050.91 3978.65
River Rch & RM=5,44,4276.354
  546.87 1004.89  1474.8  2067.7 4013.09
River Rch & RM=5,44, 4178.23
  664.43 1226.13 1806.86 2544.47 4997.17
River Rch & RM=5,44, 3981.58
  668.57 1233.94 1818.62 2561.38 5032.29
River Rch & RM=5,44,3902.645
  673.31 1242.87 1832.05 2580.72 5072.45
River Rch & RM=5,44,3685.439
  681.59  1258.5 1855.57 2614.57  5142.8
River Rch & RM=5,44, 3587.01
  683.96 1262.97 1862.29 2624.24 5162.92
River Rch & RM=5,44,3488.581
   688.1 1270.78 1874.05 2641.17 5198.13
River Rch & RM=5,44,3390.151
  693.42 1280.83 1889.17 2662.95 5243.44
River Rch & RM=5,44,3291.722
  696.38 1286.41 1897.57 2675.05 5268.63
River Rch & RM=5,44,3193.293
  702.29 1297.57 1914.37 2699.25 5319.04
River Rch & RM=5,44,2996.435
   739.5 1367.87 2020.28 2851.91 5637.51
River Rch & RM=5,44,2898.006
  742.45 1373.45 2028.69 2864.04 5662.86
River Rch & RM=5,44,2799.577
  745.99 1380.14 2038.78  2878.6 5693.28
River Rch & RM=5,44,2602.719
   751.3 1390.18 2053.92 2900.44 5738.95
River Rch & RM=5,44, 2504.29
   757.2 1401.34 2070.74 2924.71 5789.72
River Rch & RM=5,44,2405.861
  769.59 1424.76 2106.07  2975.7 5896.47
River Rch & RM=5,44,2307.432
  771.35 1428.11 2111.11 2982.99 5911.73
River Rch & RM=5,44,2209.003
  779.02 1442.61 2132.99 3014.57 5977.92
River Rch & RM=5,44,2110.574
  783.73 1451.53 2146.45 3034.01 6018.68
River Rch & RM=5,44,1701.407
  807.88 1497.24 2215.47 3133.72 6227.93
River Rch & RM=5,44,1442.434
  822.59 1525.11 2257.56 3194.57 6355.83
River Rch & RM=5,44,1399.521
  827.88 1535.15 2272.72 3216.48 6401.92
River Rch & RM=5,44,810.1993
  851.99 1580.84 2341.78 3316.38 6612.28
River Rch & RM=5,44,377.3171
  883.71 1641.02 2432.79 3448.11  6890.2
River Rch & RM=5,44,142.7915
  888.99 1651.04 2447.96 3470.08 6936.62
Boundary for River Rch & Prof#=5,44,1
Up Type= 0
Dn Type= 2
Boundary for River Rch & Prof#=5,44,2
Up Type= 0
Dn Type= 2
Boundary for River Rch & Prof#=5,44,2
Up Type= 0
Dn Type= 2
Boundary for River Rch & Prof#=5,44,2
Up Type= 0
Dn Type= 2
Boundary for River Rch & Prof#=5,44,2
Up Type= 0
Dn Type= 2

--- 5_ras.g01 (geometry) ---

Geom Title=5
Program Version=4.10

River Reach=5,44
Reach XY= 30
1230055.22739691839241.1395767931230005.38404869839148.793995926
1229939.55073372839115.4606743721229786.21744861839224.627313266
1229683.71748392839402.9605968911229532.05086048839357.960614601
1229405.38422787839250.4606500781229307.05092356839255.460651485
1229216.21761588839220.4606644531229163.71762893839139.627356532
1229187.30172877839017.2185919621229272.88425763838937.127413161
1229261.21758896838751.2941350831229005.38432167838440.460901072
1228842.05103407838363.7942618231228704.55106854838161.294325635
1228510.38445487838023.7943719751228475.38445812837782.961110819
1228419.55113999 837742.127791171228380.38448237837657.961150527
1227870.38462028 837251.29461889 1227587.0513683837187.961312557
1227397.05142423837192.1279834961227282.05145568837112.961343591
1227175.38482018 837107.128015091226977.05153758836849.628096959
1226940.38487824836732.128132736 1226873.7182295836675.461484756
1226872.05156168836618.7948348811226809.05967752836569.824250725

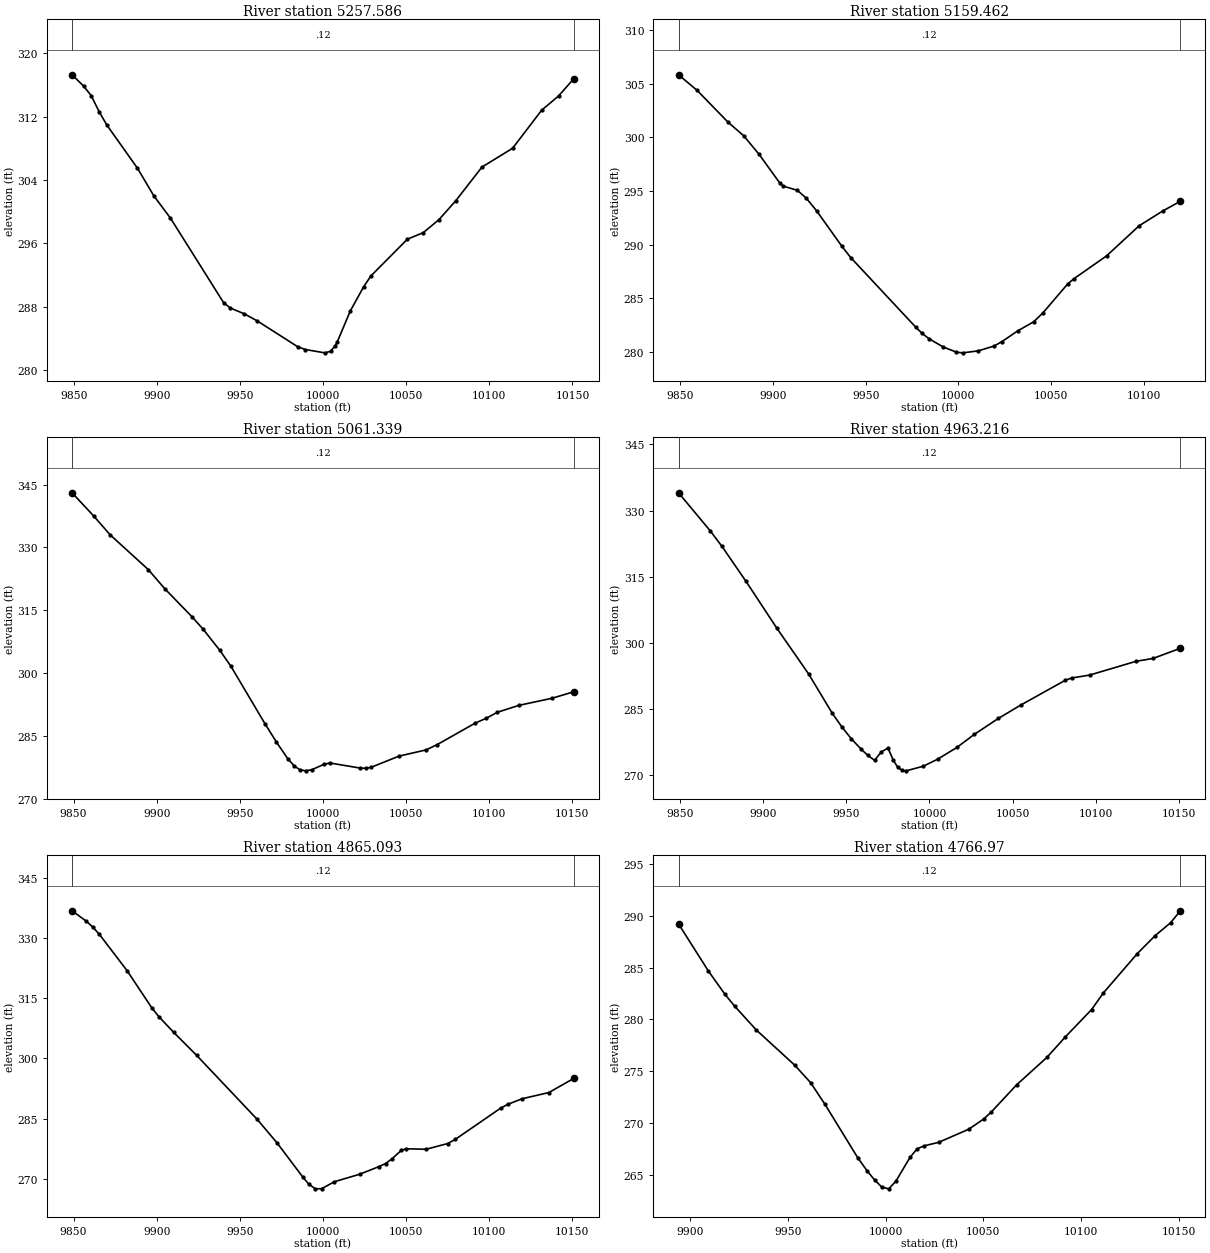
Type RM Length L Ch R = 1 ,5257.586,98.123200,98.123200,98.123200
XS GIS Cut Line= 6
 1230170.6443674839144.231622064 1230112.4448505839198.889630216
1230035.00846349839253.7807784851230007.80251485839277.981148845
1229982.03887553839315.6164521041229968.14337675839358.179485204
#Sta/Elev= 30
9849.026317.26999855.993315.83649860.502314.65279865.278312.62669869.921310.9338
9888.324305.49119898.268301.97789908.218299.17999940.188288.51159944.301287.8239
9952.556287.11659960.554286.19549984.787282.94959989.422 282.599   10001282.1834
10004.49 282.36710007.14283.037410008.47283.524810016.43287.481810024.45290.5325
10028.84291.8974 10050.8296.534810060.28297.3474 10069.8299.003710079.91301.3919
10095.58305.621310114.01 307.99410131.52312.800410141.69314.598110150.88316.7834
#Mann= 3 , 0 , 0
9849.026    0.12       09849.026    0.12       010150.88    0.12       0
#XS Ineff= 2 , 0
       0                               0
Bank Sta=9849.026,10150.88
Exp/Cntr=0.3,0.1

Type RM Length L Ch R = 1 ,5159.462,98.123200,98.123200,98.123200
XS GIS Cut Line= 6
 1230114.4850584839049.3640001861230052.37063873839121.940582827
1230024.76029208839144.7031020081230006.87432009839154.695222825
1229978.59583247839189.1161265081229952.55416581839258.560570955
#Sta/Elev= 30
9849.096305.83819859.168304.3761 9875.84301.41119884.177300.16839892.513298.4304
9903.606295.77839905.552295.46699913.195295.06869917.989294.34089923.549293.1625
9937.167289.86519941.961 288.8059977.185282.29189980.537281.73299984.317281.2282
9991.878280.4707    9999279.992310002.32279.929410010.81280.114610019.31280.5673
10023.55280.979510032.04281.980310040.54282.810810045.55283.639910058.93286.3428
10062.44 286.84810079.96288.966310097.48291.765810110.38293.162210119.71294.0495
#Mann= 3 , 0 , 0
9849.096    0.12       09849.096    0.12       010119.71    0.12       0
#XS Ineff= 2 , 0
       0                               0
Bank Sta=9849.096,10119.71
Exp/Cntr=0.3,0.1

Type RM Length L Ch R = 1 ,5061.339,98.123200,98.123200,98.123200
XS GIS Cut Line= 6
1229900.54096933838975.3826114171229902.10569894839027.716868244
1229907.96614441839068.0069105471229940.52301574839161.315220505
1229941.94508874839199.6904907521229937.38884433839270.566271699
#Sta/Elev= 30
 9849.11343.05499862.128337.50369871.975333.02029894.951324.70149904.831320.1408
9921.408313.36169928.039310.40199937.985305.39439944.687301.56939965.163287.8442
9971.989283.50179978.814279.52329982.848277.74259986.061276.89139989.692276.6138
9993.323276.891510000.64 278.17310004.29278.482410022.27277.277910025.63277.2289
   10029277.465410045.71280.127210062.13281.624610068.69282.882210091.69288.0477
10098.26289.184510104.84 290.60510117.99 292.27710137.72293.948910150.89295.5144
#Mann= 3 , 0 , 0
 9849.11    0.12       0 9849.11    0.12       010150.89    0.12       0
#XS Ineff= 2 , 0
       0                               0
Bank Sta=9849.11,10150.89
Exp/Cntr=0.3,0.1

Type RM Length L Ch R = 1 ,4963.216,98.123300,98.123300,98.123300
XS GIS Cut Line= 6
1229772.21005734839053.1154571721229790.93811826839095.389439783
1229812.45195577839131.8467948711229894.01997295839239.405266559
1229908.32462508 839269.45837493 1229920.4391564839312.631395555
#Sta/Elev= 30
 9849.07334.02699867.991325.47399875.167321.89549889.521314.03999908.212303.3562
9927.259293.01849941.599  284.059947.238281.03449952.877278.36359958.919275.9454
9962.953274.53629966.987273.4252 9971.02275.33019975.054276.20019978.207273.4938
9980.803271.90649983.422 271.1789985.912271.04939996.262272.092710004.86273.6747
10016.58276.367110026.86279.280110041.51282.934110054.95285.955410081.82291.5873
10085.45292.068410096.35292.739810124.22295.853410134.44296.502710150.89298.7968
#Mann= 3 , 0 , 0
 9849.07    0.12       0 9849.07    0.12       010150.89    0.12       0
#XS Ineff= 2 , 0
       0                               0
Bank Sta=9849.07,10150.89
Exp/Cntr=0.3,0.1

Type RM Length L Ch R = 1 ,4865.093,98.123200,98.123200,98.123200
XS GIS Cut Line= 6
1229669.82593234839138.4398035331229687.42706552839167.920678495
1229716.43138163839200.6859444861229831.27682992839278.578754288
1229860.17330033839305.9642580181229886.48143055839342.222913964
#Sta/Elev= 30
9849.099336.73869857.757334.11529861.578332.65859865.399330.93619882.218321.8105
9897.154312.50919901.336310.35899910.286 306.4319924.016300.73959960.494284.7758
9972.417 278.9279987.751270.50139991.408268.68289995.424267.49459999.257267.5345
10006.86269.260410022.08271.131610033.63273.016710037.69273.800810041.46274.9405
10047.03277.047210049.86277.471610062.04277.351410075.12 278.78410079.64279.8214
10106.87287.586810111.15288.528310119.62289.9117 10135.9291.478410150.92 295.009
#Mann= 3 , 0 , 0
9849.099    0.12       09849.099    0.12       010150.92    0.12       0
#XS Ineff= 2 , 0
       0                               0
Bank Sta=9849.099,10150.92
Exp/Cntr=0.3,0.1

Type RM Length L Ch R = 1 , 4766.97,98.123200,98.123200,98.123200
XS GIS Cut Line= 6
1229656.77091029 839267.68980585  1229680.944426839299.228376582
1229703.68806815839316.1588189451229763.62260136839344.788827837
1229809.16322502839376.605478019 1229850.1446937839428.849967554
#Sta/Elev= 30
9894.003289.22049909.225284.69339917.702 282.4469922.717281.28679933.822278.9846
9953.397275.60479961.577273.91139968.915271.82669985.762266.65259990.728265.3448
9994.363264.51779997.999263.837410001.61 263.65710005.25 264.39410012.53266.7012
10016.17267.527310019.81267.808210027.09268.141410042.51269.403810050.27270.4022
10054.15271.080710067.17 273.71210082.58276.341810091.85278.286610105.47280.9625
10111.43282.552210128.86286.360810137.95 288.084 10145.9289.336110150.87290.4893
#Mann= 3 , 0 , 0
9894.003    0.12       09894.003    0.12       010150.87    0.12       0
#XS Ineff= 2 , 0
       0                               0
Bank Sta=9894.003,10150.87
Exp/Cntr=0.3,0.1

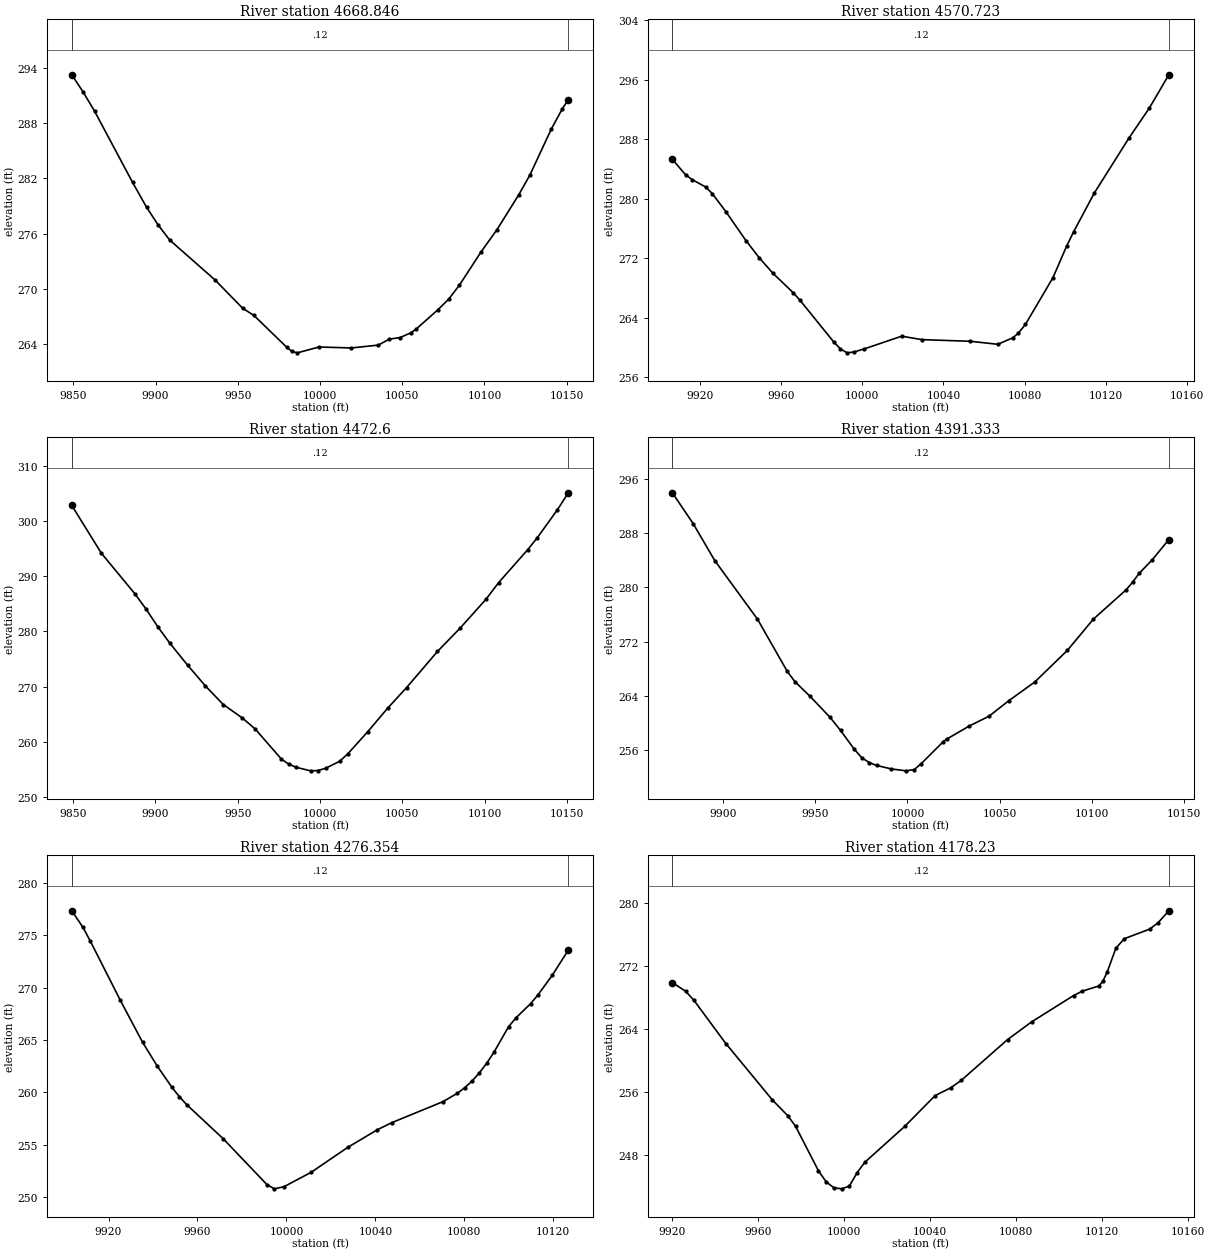
Type RM Length L Ch R = 1 ,4668.846,98.123200,98.123200,98.123200
XS GIS Cut Line= 6
1229640.85636283 839257.61259133  1229666.106065839323.990473966
1229676.66963758839364.7295257041229679.27939034  839391.7314491
1229678.78014596839424.4650275431229685.92438389839553.179229978
#Sta/Elev= 30
9849.078 293.2629855.895291.41059862.916289.31319886.034281.57299894.507278.8841
9901.528276.96849908.548275.3239 9936.06270.99859953.007267.90049959.786267.1315
9979.628263.69229982.924263.2166 9986.22263.06539999.363263.699210019.06263.5974
10035.48263.906210042.06264.550310048.63264.7218 10055.2265.237710058.48265.6472
10071.63267.7344 10078.2268.889910084.77270.415610097.92274.029410107.64 276.456
10120.92280.255410127.49282.330110140.63287.3626 10147.2289.524810150.97290.5608
#Mann= 3 , 0 , 0
9849.078    0.12       09849.078    0.12       010150.97    0.12       0
#XS Ineff= 2 , 0
       0                               0
Bank Sta=9849.078,10150.97
Exp/Cntr=0.3,0.1

Type RM Length L Ch R = 1 ,4570.723,98.123200,98.123200,98.123200
XS GIS Cut Line= 6
 1229605.8162159839267.3006036881229600.75849539839316.408574447
1229593.09637538839358.9216973041229592.46391988839360.819063902
1229586.46102938839389.8487441841229555.49623513839506.143483117
#Sta/Elev= 30
9906.434285.31249912.995283.20219916.293 282.5559922.889281.56779926.188280.6602
9932.784278.26569942.678274.36569949.275 272.0349955.872269.99229965.873267.3706
9969.207266.36519985.875260.73399989.209259.77399992.543259.24839995.876259.3603
   10001259.781910019.37261.487410029.43261.025810053.18260.803510066.76260.3981
10074.19261.278810076.94  261.9210080.34263.065610093.92 269.37410100.71273.6457
 10104.1275.545110114.29280.764610131.26288.124310141.45292.224210150.99296.6791
#Mann= 3 , 0 , 0
9906.434    0.12       09906.434    0.12       010150.99    0.12       0
#XS Ineff= 2 , 0
       0                               0
Bank Sta=9906.434,10150.99
Exp/Cntr=0.3,0.1

Type RM Length L Ch R = 1 ,  4472.6,81.266500,81.266500,81.266500
XS GIS Cut Line= 6
1229568.24838048839204.0164329411229556.02217432839247.166155297
1229537.47933084 839288.982552331229519.16148488839317.782790347
1229474.04980577839371.2888151421229426.23091829839466.868663092
#Sta/Elev= 30
9849.145302.81729867.143294.15559887.603286.78169894.446283.98529901.624280.7603
9908.802277.85589919.568 273.8849930.335270.14469941.216266.77279952.881264.3254
9960.657262.33849976.539256.89759980.973255.99659985.408 255.4189994.277254.7704
9998.711254.828910003.37 255.22510011.97256.498110016.88 257.83810029.01261.8504
10041.14266.115410052.61 269.83510071.41276.380910085.38280.671710100.91285.8358
10108.59288.844610126.22294.787810132.02296.941110144.29302.022610150.94305.1083
#Mann= 3 , 0 , 0
9849.145    0.12       09849.145    0.12       010150.94    0.12       0
#XS Ineff= 2 , 0
       0                               0
Bank Sta=9849.145,10150.94
Exp/Cntr=0.3,0.1

Type RM Length L Ch R = 1 ,4391.333,114.979900,114.979900,114.979900
XS GIS Cut Line= 6
1229508.10972133839185.6439042841229494.01368159839207.386226952
1229481.64207077839227.563055649 1229465.4612785839249.299275652
1229424.77638799839307.1716820451229379.63749909839420.018904284
#Sta/Elev= 30
9872.622293.96679883.876289.43499895.606283.97059918.743275.33059934.886 267.626
9938.976 266.1329947.156263.97369958.054 260.8579963.759258.9189 9971.26256.1229
9975.271254.88539979.281254.18869983.292253.76229991.312253.24159999.333252.9633
10003.69253.158510007.35253.999710019.39257.258210021.22257.6368 10033.6259.5886
 10044.2261.0234 10054.8263.285510068.93266.0568 10086.6270.720910100.73275.3432
 10118.4279.643210121.94280.770310125.47 282.07610132.54284.065410141.58287.0625
#Mann= 3 , 0 , 0
9872.622    0.12       09872.622    0.12       010141.58    0.12       0
#XS Ineff= 2 , 0
       0                               0
Bank Sta=9872.622,10141.58
Exp/Cntr=0.3,0.1

Type RM Length L Ch R = 1 ,4276.354,98.123200,98.123200,98.123200
XS GIS Cut Line= 6
1229358.81552097839163.897359993 1229351.7539212839199.383722974
1229347.59783935839253.0651303361229346.61808506839258.452341842
1229346.19902694839260.4079466831229354.01179821839385.917955388
#Sta/Elev= 30
  9903.5277.3414 9908.54  275.759911.885274.41719925.266268.80869935.301264.7817
9941.954262.48849948.535260.46719951.826259.58649955.116258.8235 9971.57255.5597
9991.314251.16119994.619250.7704    9999250.982810011.16252.354910027.59254.7348
10040.74256.400310047.32257.089210070.33259.0946 10076.9259.907510080.19260.4341
10083.48261.076610086.76261.855810090.05262.767110093.34263.833110099.91 266.269
 10103.2 267.10810109.77268.462510113.06269.289910119.63271.209110126.75273.5835
#Mann= 3 , 0 , 0
  9903.5    0.12       0  9903.5    0.12       010126.75    0.12       0
#XS Ineff= 2 , 0
       0                               0
Bank Sta=9903.5,10126.75
Exp/Cntr=0.3,0.1

Type RM Length L Ch R = 1 , 4178.23,98.123200,98.123200,98.123200
XS GIS Cut Line= 6
1229286.57401812839163.4269739091229272.15350109839189.644423574
 1229244.2856279839253.6624775081229228.98076692839284.663046062
  1229208.174483839320.6449270991229177.76310804839366.535022452
#Sta/Elev= 30
9920.047269.89669926.225   268.8 9929.97267.69169944.947262.15479966.628254.9849
 9973.78252.98479977.355251.66559988.033245.99519991.659 244.5849995.234243.8452
 9998.81243.714810002.39244.061110005.97 245.76510009.56247.084110028.09251.6311
10042.28255.5489 10049.6 256.55210054.36257.469310075.95262.655610087.32264.9386
10106.67268.247410110.61268.795410118.48269.472110120.36270.099710122.41271.3013
10126.35274.266110130.29275.471810142.09 276.68610146.03277.507410150.98279.0123
#Mann= 3 , 0 , 0
9920.047    0.12       09920.047    0.12       010150.98    0.12       0
#XS Ineff= 2 , 0
       0                               0
Bank Sta=9920.047,10150.98
Exp/Cntr=0.3,0.1

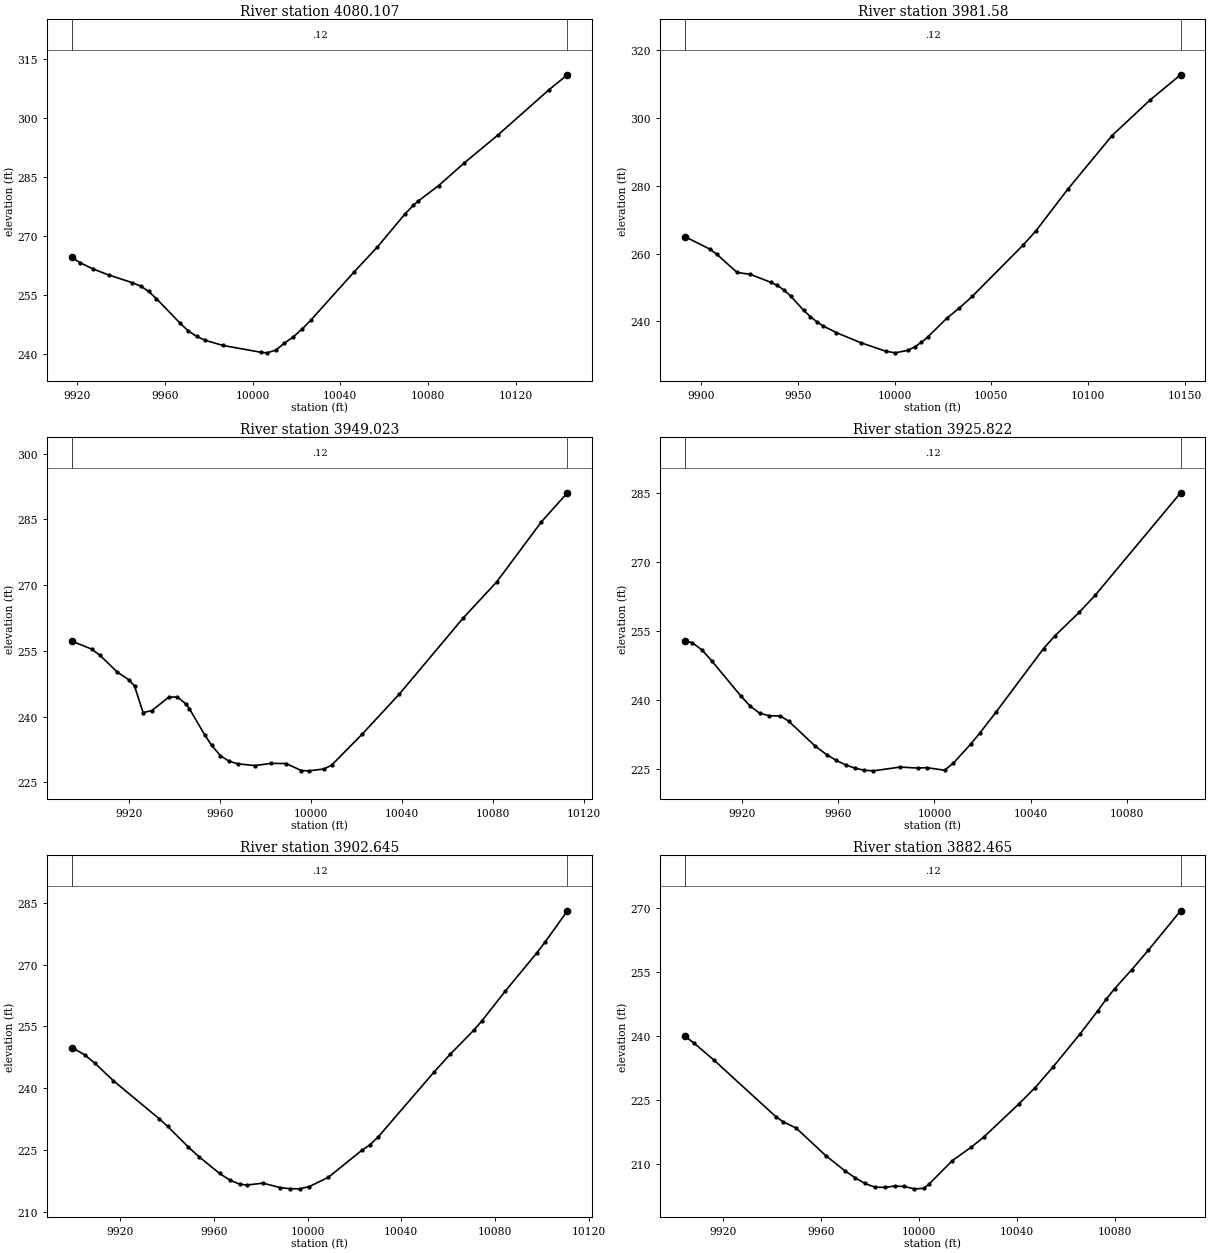
Type RM Length L Ch R = 1 ,4080.107,98.526700,98.526700,98.526700
XS GIS Cut Line= 6
1229249.48060586839137.7246974041229200.51574022839160.107942133
1229177.74305215839175.7930766261229176.13469991839176.981858797
1229150.99593575839194.9950251141229056.28393725839254.150625249
#Sta/Elev= 30
 9917.51264.51889921.329263.15059927.263261.57219934.478260.02019945.003258.1125
9948.907257.23899952.514255.88629956.122254.04219966.944247.77269970.551245.8818
9974.452244.43889978.436243.43879986.403242.142310003.92240.391410006.44240.2601
10010.48240.914710014.51242.706610018.55244.305610022.58246.304410026.62248.6075
10046.18260.756810056.87267.139110069.39275.475510073.26277.739410075.45278.8009
10084.86282.769510096.47288.487810111.94295.647610135.15307.098310143.59310.9211
#Mann= 3 , 0 , 0
 9917.51    0.12       0 9917.51    0.12       010143.59    0.12       0
#XS Ineff= 2 , 0
       0                               0
Bank Sta=9917.51,10143.59
Exp/Cntr=0.3,0.1

Type RM Length L Ch R = 1 , 3981.58,32.557600,32.557600,32.557600
XS GIS Cut Line= 6
1229275.88679821839113.565524832 1229229.2288121839097.289483165
1229162.60260628839080.754165472 1229120.9104607839075.763832369
1229070.58493699839074.1125345261229024.81796218 839077.18519344
#Sta/Elev= 30
9891.582265.0036 9904.62 261.2889908.094259.78459918.519254.46459925.468 253.871
9935.892251.55839939.367250.61049942.797249.26539946.187247.49549952.968243.2753
9956.359241.44799959.749239.9033 9963.14238.63819969.921236.68589982.502233.7143
9995.508231.195510000.38230.731810007.07231.5092 10010.4232.510410013.71233.7828
10017.01  235.3410026.92240.908210033.53243.991610040.14  247.3910066.48262.5631
10073.04266.703510089.45278.950110112.45294.853510132.18305.381310147.88 312.774
#Mann= 3 , 0 , 0
9891.582    0.12       09891.582    0.12       010147.88    0.12       0
#XS Ineff= 2 , 0
       0                               0
Bank Sta=9891.582,10147.88
Exp/Cntr=0.3,0.1

Type RM Length L Ch R = 1 ,3949.023,23.200900,23.200900,23.200900
XS GIS Cut Line= 5
1229271.15589543839095.864425295 1229197.9788121839054.458175295
1229161.27504404839047.3784157021229110.94952032839045.727117859
1229065.18254551839048.799776773
#Sta/Elev= 30
9894.917257.22569903.626255.42179907.396253.95699914.935250.15399919.946248.4404
9922.474 246.9969926.244240.94479930.013241.36619937.553244.45879941.322244.4946
9945.092242.89229946.595241.80769953.257235.87969956.401233.4475 9960.17231.1317
 9963.94229.8625 9967.71229.26869975.249228.85599982.357229.3509 9989.04229.3223
9995.723227.72319999.064227.654810005.75228.083610009.09228.983110022.35235.9591
10038.76245.152410066.73262.450210081.46270.684910101.19284.4501 10112.6291.0568
#Mann= 3 , 0 , 0
9894.917    0.12       09894.917    0.12       0 10112.6    0.12       0
#XS Ineff= 2 , 0
       0                               0
Bank Sta=9894.917,10112.6
Exp/Cntr=0.3,0.1

Type RM Length L Ch R = 1 ,3925.822,23.177100,23.177100,23.177100
XS GIS Cut Line= 6
1229269.35874314839083.3292398371229225.18956281839052.381688945
1229205.98616317839040.3276529161229167.33459513 839020.45178233
1229130.76135471839008.3030640231229084.20420256839000.542165015
#Sta/Elev= 30
9896.425252.7494 9899.48252.35159903.486250.78899907.492248.4431 9919.51240.8531
9923.516238.57119927.522236.99689931.528236.46789936.083236.4421 9939.54235.2768
9950.357229.9433 9955.37227.98789959.249226.76449963.127225.79129967.006225.0824
9970.884224.62839974.678224.50029985.745225.32189993.124225.10229996.813225.1932
10004.19224.636410007.88 226.17110015.26230.428310018.79232.670910025.71237.3553
10045.33251.096210049.91253.795510060.08258.942910066.73262.658410102.23284.9516
#Mann= 3 , 0 , 0
9896.425    0.12       09896.425    0.12       010102.23    0.12       0
#XS Ineff= 2 , 0
       0                               0
Bank Sta=9896.425,10102.23
Exp/Cntr=0.3,0.1

Type RM Length L Ch R = 1 ,3902.645,20.179400,20.179400,20.179400
XS GIS Cut Line= 5
1229270.89547877839075.8123419621229215.42672877839025.291508628
1229188.34339543839003.9373419621229160.73922877838993.260258628
 1229090.1663121838976.333175295
#Sta/Elev= 30
9899.306 249.7869900.331249.57869904.769248.11439909.206246.05199917.066241.8161
9936.556232.6216 9940.27230.71539949.145225.68829953.583223.38529962.459219.2953
9966.896217.65189971.334216.63289974.334216.49979980.938216.94729988.221215.8773
9992.399215.60519996.577215.562510000.76216.127110008.82218.337910023.14224.9035
10026.65226.246110030.17228.170310054.13243.984810060.87248.2086   10071254.0775
10074.37256.283810084.49263.599710097.99272.907710101.36275.400710110.99283.0719
#Mann= 3 , 0 , 0
9899.306    0.12       09899.306    0.12       010110.99    0.12       0
#XS Ineff= 2 , 0
       0                               0
Bank Sta=9899.306,10110.99
Exp/Cntr=0.3,0.1

Type RM Length L Ch R = 1 ,3882.465,98.597900,98.597900,98.597900
XS GIS Cut Line= 6
1229282.78783988839049.4451544621229248.65561814839022.348337059
1229204.48643781838991.4007861671229185.28303817838979.346750138
1229146.63147013838959.4708795521229110.05822971838947.322161246
#Sta/Elev= 30
9904.624239.91079908.209238.33019916.587234.22689941.721221.00439944.771219.7845
9950.016218.33299962.034211.88649970.046208.24369974.052206.68069978.058205.3369
9982.064204.4774 9986.07204.41819990.224204.73249994.082204.63279998.088204.0773
10002.09204.182810004.14205.1569 10013.7210.710710021.46213.885110026.55216.2484
 10040.9 224.04310047.45227.821210054.83 232.72710065.89240.521810072.96245.8215
10076.41248.548110079.87 251.03910086.79255.4641 10093.7260.134110106.81269.3391
#Mann= 3 , 0 , 0
9904.624    0.12       09904.624    0.12       010106.81    0.12       0
#XS Ineff= 2 , 0
       0                               0
Bank Sta=9904.624,10106.81
Exp/Cntr=0.3,0.1

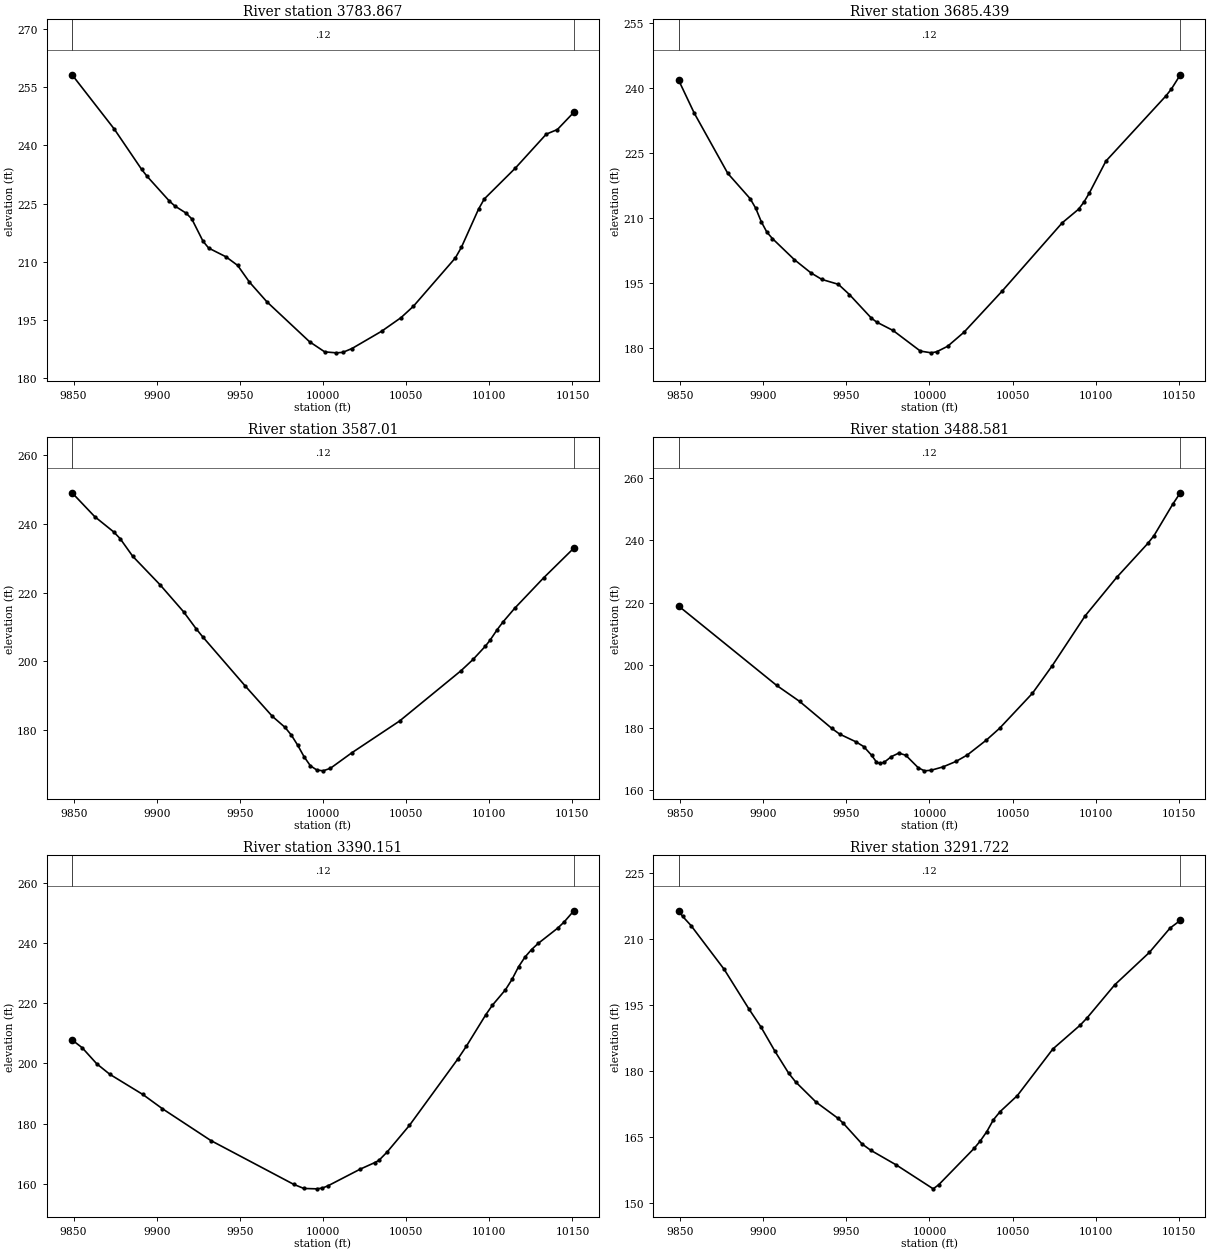
Type RM Length L Ch R = 1 ,3783.867,98.429000,98.429000,98.429000
XS GIS Cut Line= 6
1229420.21083064 838963.36060846 1229382.0165707838962.766483826
 1229334.5326659838952.4608777021229267.18721203838928.068492525
  1229201.327602838891.4398822451229135.73168292838875.034909973
#Sta/Elev= 30
9849.098258.15239874.502244.17149890.961 233.793 9894.29231.98979907.608225.6599
9910.937 224.3829917.653222.55959921.058221.09319927.867215.31219931.272213.5538
9941.665211.31419948.695209.09599955.724204.82829966.268199.7342 9991.93189.4568
10001.06186.849710008.01186.6025 10011.9 186.72210017.45187.715910035.25192.1569
10046.92195.656910054.34198.569710079.63211.034810083.24213.753210093.56223.5876
   10097226.194410115.74234.157710134.29242.878310140.97244.062810150.88248.5085
#Mann= 3 , 0 , 0
9849.098    0.12       09849.098    0.12       010150.88    0.12       0
#XS Ineff= 2 , 0
       0                               0
Bank Sta=9849.098,10150.88
Exp/Cntr=0.3,0.1

Type RM Length L Ch R = 1 ,3685.439,98.429000,98.429000,98.429000
XS GIS Cut Line= 6
1229423.71979833838812.9915801541229371.69827332838824.718290712
1229318.91500164838831.5355449471229275.55092077838833.200623644
1229194.59198725838834.1308397761229123.72764868 838838.77088004
#Sta/Elev= 30
9849.055241.85369858.512234.19389878.691220.27639892.144214.44089895.507212.2272
 9898.87209.08999902.233206.68569905.544205.22319918.776 200.342  9928.7197.3017
9935.316195.78239945.241194.65179951.857192.30269965.018186.87479968.301185.9223
9978.151183.98929994.567179.232810001.13178.828110004.41179.078910010.98180.3473
10020.82183.594510043.79193.100810079.88208.845210089.74211.997710093.03213.6781
10096.32215.808510106.18223.103710142.35238.185710145.63239.779110150.98 243.052
#Mann= 3 , 0 , 0
9849.055    0.12       09849.055    0.12       010150.98    0.12       0
#XS Ineff= 2 , 0
       0                               0
Bank Sta=9849.055,10150.98
Exp/Cntr=0.3,0.1

Type RM Length L Ch R = 1 , 3587.01,98.429000,98.429000,98.429000
XS GIS Cut Line= 6
1229383.54495907838662.7854992161229254.62891499838739.446989218
1229252.95750406838740.5453450421229202.12280316838771.113027512
1229160.74302958838790.642356526  1229118.378019838805.424913563
#Sta/Elev= 30
9849.012249.12449862.626242.18539874.077237.72299877.894235.79999885.529230.6231
9901.941222.34369916.065214.50199923.699209.50269927.517207.24069953.292192.8191
9969.505184.03779977.139180.82539980.956178.56129984.773175.6249 9988.59172.2796
9992.407169.62939996.224168.412710000.07168.156710004.47168.9061 10017.2173.3678
10046.03182.651310083.06197.322110090.32200.605410097.57 204.391 10100.5206.1828
10104.83209.284710108.35211.5348 10115.3 215.47110132.68224.320910150.94233.0096
#Mann= 3 , 0 , 0
9849.012    0.12       09849.012    0.12       010150.94    0.12       0
#XS Ineff= 2 , 0
       0                               0
Bank Sta=9849.012,10150.94
Exp/Cntr=0.3,0.1

Type RM Length L Ch R = 1 ,3488.581,98.429000,98.429000,98.429000
XS GIS Cut Line= 6
1229296.38391876838586.0068181121229251.80295995838624.693386525
1229195.96852171838676.5459514511229163.75911862838691.609263302
1229099.38758493 838735.062642861229052.87220645838760.750830906
#Sta/Elev= 30
9849.059218.94639908.085193.55179921.855188.45389941.269179.80589945.962177.9885
9955.604175.56329960.425174.01529965.247171.19689968.134169.02669970.068168.6165
9972.611168.92159977.088170.77919981.566171.91719985.754171.23079993.235167.2447
9996.976166.2438   10001 166.43110008.18167.512210015.92169.2401 10022.8171.3203
10034.26176.085710042.17179.836110061.97191.044510073.84 199.83210093.63215.7641
10112.59228.051410131.33238.923910135.08241.430210146.32251.443210150.91255.1224
#Mann= 3 , 0 , 0
9849.059    0.12       09849.059    0.12       010150.91    0.12       0
#XS Ineff= 2 , 0
       0                               0
Bank Sta=9849.059,10150.91
Exp/Cntr=0.3,0.1

Type RM Length L Ch R = 1 ,3390.151,98.429100,98.429100,98.429100
XS GIS Cut Line= 6
1229232.07755006838504.1930716581229145.55663579838582.686210426
1229133.33219196838598.7539934511229119.99235236838627.116488525
1229102.60037768838646.8993697711229015.95252718838709.481268224
#Sta/Elev= 30
9849.069207.78579855.193205.17469863.947199.84729871.794196.3706 9891.62189.6871
9903.339184.98559932.565174.3899 9982.32159.87689988.471158.50419996.083158.3775
9999.646158.6341 10003.2159.445310022.39164.919810031.13167.088210033.58167.8087
10038.55170.594810051.99179.448210080.99201.398310086.23205.717710097.92  216.17
10101.84219.2886 10109.7224.417510113.63227.838910117.56232.032610121.48235.2909
10125.41237.772410129.34239.778810141.12244.872510144.96246.889310150.85250.6324
#Mann= 3 , 0 , 0
9849.069    0.12       09849.069    0.12       010150.85    0.12       0
#XS Ineff= 2 , 0
       0                               0
Bank Sta=9849.069,10150.85
Exp/Cntr=0.3,0.1

Type RM Length L Ch R = 1 ,3291.722,98.429000,98.429000,98.429000
XS GIS Cut Line= 6
1229202.54173106838445.404363757 1229126.4227496838507.545258533
1229097.87302952838523.5180843171229067.41458681838531.365451856
1229049.62475898838539.9177963391228953.58773817838610.984241653
#Sta/Elev= 30
9849.083216.32229851.596215.03289856.584212.97319876.537203.02159891.502193.9766
 9898.72 189.8949907.137 184.3829915.352179.4186 9919.46177.47569931.783172.8747
9945.027169.18339948.145168.08169959.423163.37539964.632161.94659980.124158.5818
10002.28153.170710005.64154.117910026.98162.400610030.62164.059310034.52166.1697
 10038.5168.860310042.47170.690510052.88174.345510074.26184.938310090.64 190.331
 10094.8191.980810111.45199.499610132.26206.847910144.74212.389810150.92214.1407
#Mann= 3 , 0 , 0
9849.083    0.12       09849.083    0.12       010150.92    0.12       0
#XS Ineff= 2 , 0
       0                               0
Bank Sta=9849.083,10150.92
Exp/Cntr=0.3,0.1

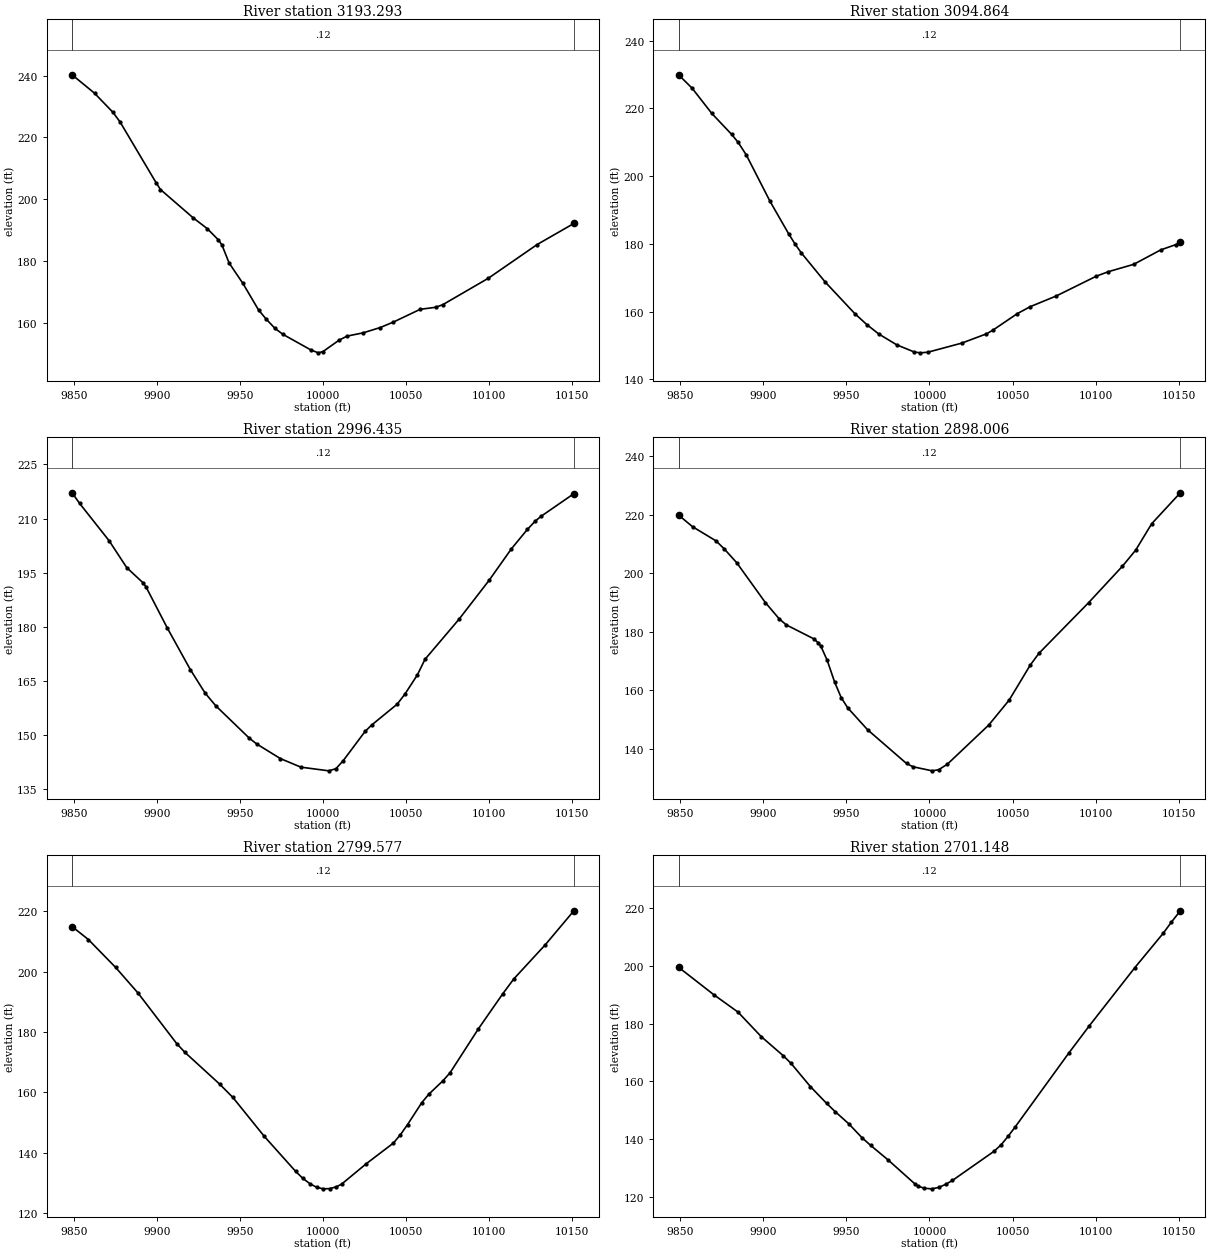
Type RM Length L Ch R = 1 ,3193.293,98.429000,98.429000,98.429000
XS GIS Cut Line= 6
1229121.58301251838346.6258921121229050.77001146838426.959698891
1229019.45073611838456.2477348231228993.46112215838480.371105343
1228948.42670201838534.6583146931228917.21464388838568.389036412
#Sta/Elev= 30
9849.031240.24179862.528234.28839873.573228.13079877.946224.96329899.814205.1293
9902.221203.14069921.681194.07689930.428190.46249936.951186.91469939.175185.2353
9943.549179.35289951.836172.76479961.225164.20159965.717161.30159971.133158.2242
9975.937156.29319992.668151.2767 9997.16150.323210000.04150.742310009.72154.4306
10014.52155.738810024.12156.779710034.46158.505510042.33160.264110058.46164.3927
10067.91165.061510072.17165.919710099.56174.464210128.87185.347910150.96192.1615
#Mann= 3 , 0 , 0
9849.031    0.12       09849.031    0.12       010150.96    0.12       0
#XS Ineff= 2 , 0
       0                               0
Bank Sta=9849.031,10150.96
Exp/Cntr=0.3,0.1

Type RM Length L Ch R = 1 ,3094.864,98.429000,98.429000,98.429000
XS GIS Cut Line= 6
1229004.13629808838292.618225693 1228964.5705518838355.912139952
 1228928.5379235838439.9025955121228910.31057633 838475.00751912
1228887.21464371838509.3974167241228851.71558034838551.154116217
#Sta/Elev= 30
9849.046229.95949857.235225.98459869.087218.52399880.939212.3796 9884.89210.0116
9889.814206.27229904.088192.57669915.386182.90199919.152  179.969922.918177.3361
9937.265168.74869955.146 159.3829962.298156.1753 9969.45153.40619980.325150.1838
9990.907148.06269994.484  147.82    9999148.000910019.51150.703910034.29153.4287
10037.99154.461410052.78159.375910060.55161.441410076.36164.631710100.42170.4725
 10107.7171.805110122.89 173.96410139.18 178.23710148.22179.786110150.93180.4526
#Mann= 3 , 0 , 0
9849.046    0.12       09849.046    0.12       010150.93    0.12       0
#XS Ineff= 2 , 0
       0                               0
Bank Sta=9849.046,10150.93
Exp/Cntr=0.3,0.1

Type RM Length L Ch R = 1 ,2996.435,98.429000,98.429000,98.429000
XS GIS Cut Line= 6
1228954.39113792838259.9729305571228862.86534609838360.266447343
1228852.80378201838372.9594885961228831.39618708838398.189382388
1228794.37053157838435.2912969961228747.25156354838479.284984938
#Sta/Elev= 30
9849.023 217.1559853.568214.20299871.334203.84729881.926196.4049 9891.66192.2291
9893.543191.04079906.261179.72879920.192 168.1349929.076161.63549935.464158.1166
9955.725149.10959960.167147.50569974.401143.46529986.708141.093910003.52 140.072
10007.82140.677310012.12142.856410025.32150.985810029.33152.781610044.64 158.553
10049.28161.321710056.78166.642910061.41170.997710081.79182.054810099.91192.8491
10113.37201.609910122.97  206.9810127.78209.325310131.33210.660710150.97216.9052
#Mann= 3 , 0 , 0
9849.023    0.12       09849.023    0.12       010150.97    0.12       0
#XS Ineff= 2 , 0
       0                               0
Bank Sta=9849.023,10150.97
Exp/Cntr=0.3,0.1

Type RM Length L Ch R = 1 ,2898.006,98.429000,98.429000,98.429000
XS GIS Cut Line= 6
1228922.05873313838198.962814342 1228888.7818714 838229.07650003
1228852.89282213838257.4802493341228824.63409594838276.682296773
1228746.37939898838325.1736332141228677.54249635838375.162375421
#Sta/Elev= 30
9849.023219.82659857.453215.85029871.609211.00479876.498208.29549884.002203.5944
9901.277189.97359909.645184.40149913.829182.37719930.565177.56679933.238176.1507
9934.749 175.0119938.524170.21879942.938162.87789946.904157.55979950.871  154.04
9962.771146.60889986.212135.09029990.067133.982510001.66132.586110005.52132.9627
10010.79 134.849 10035.7148.217610047.98156.712910060.61168.6063 10065.9 172.671
10095.73189.911310116.01202.296710124.12  207.8710133.74216.867510150.97227.4214
#Mann= 3 , 0 , 0
9849.023    0.12       09849.023    0.12       010150.97    0.12       0
#XS Ineff= 2 , 0
       0                               0
Bank Sta=9849.023,10150.97
Exp/Cntr=0.3,0.1

Type RM Length L Ch R = 1 ,2799.577,98.429100,98.429100,98.429100
XS GIS Cut Line= 6
1228856.31909918 838105.759721941228764.64278085838190.570778499
1228753.20400766838203.2466974791228742.26969629838219.634884144
1228733.19685319838229.1724519721228635.42005822838310.400459894
#Sta/Elev= 30
9849.023214.88059858.819210.59739875.249 201.3599888.657192.92789911.962176.1856
9916.794173.33559937.821162.76419945.781158.35339964.638145.50939983.534 133.903
9987.953131.54559992.223129.77929996.168128.646710000.07128.116510004.01128.1834
10007.98128.777510011.19129.660510025.97136.388210042.37143.249910046.63 146.048
 10050.9149.374910059.43156.608310063.69159.424710072.18163.861610076.49 166.524
10093.55181.072110108.12192.592210114.88197.594610133.79208.866510150.97220.1028
#Mann= 3 , 0 , 0
9849.023    0.12       09849.023    0.12       010150.97    0.12       0
#XS Ineff= 2 , 0
       0                               0
Bank Sta=9849.023,10150.97
Exp/Cntr=0.3,0.1

Type RM Length L Ch R = 1 ,2701.148,98.429000,98.429000,98.429000
XS GIS Cut Line= 6
1228776.00361993838029.8933267521228714.58201725838096.581187822
1228678.18072167838143.3915657921228676.98072172838144.991565829
1228640.09448364838191.4408853351228577.40256183838256.903375844
#Sta/Elev= 30
9849.038199.50979870.286 189.9779884.815183.96649898.779175.4785 9912.16168.7867
 9916.62166.2701  9928.4158.13589938.085152.36119943.262149.47789951.443145.2687
9959.296140.4993 9964.64137.76059975.329132.63229991.363124.36239993.004123.7186
9996.708 122.92110001.29122.711310005.48123.188810009.67124.243310013.86125.6336
   10039135.776710043.19138.016810047.38140.954910051.57144.148910083.85169.7663
10096.25179.257210123.51199.318410140.77211.369410145.52215.093510150.95 219.074
#Mann= 3 , 0 , 0
9849.038    0.12       09849.038    0.12       010150.95    0.12       0
#XS Ineff= 2 , 0
       0                               0
Bank Sta=9849.038,10150.95
Exp/Cntr=0.3,0.1