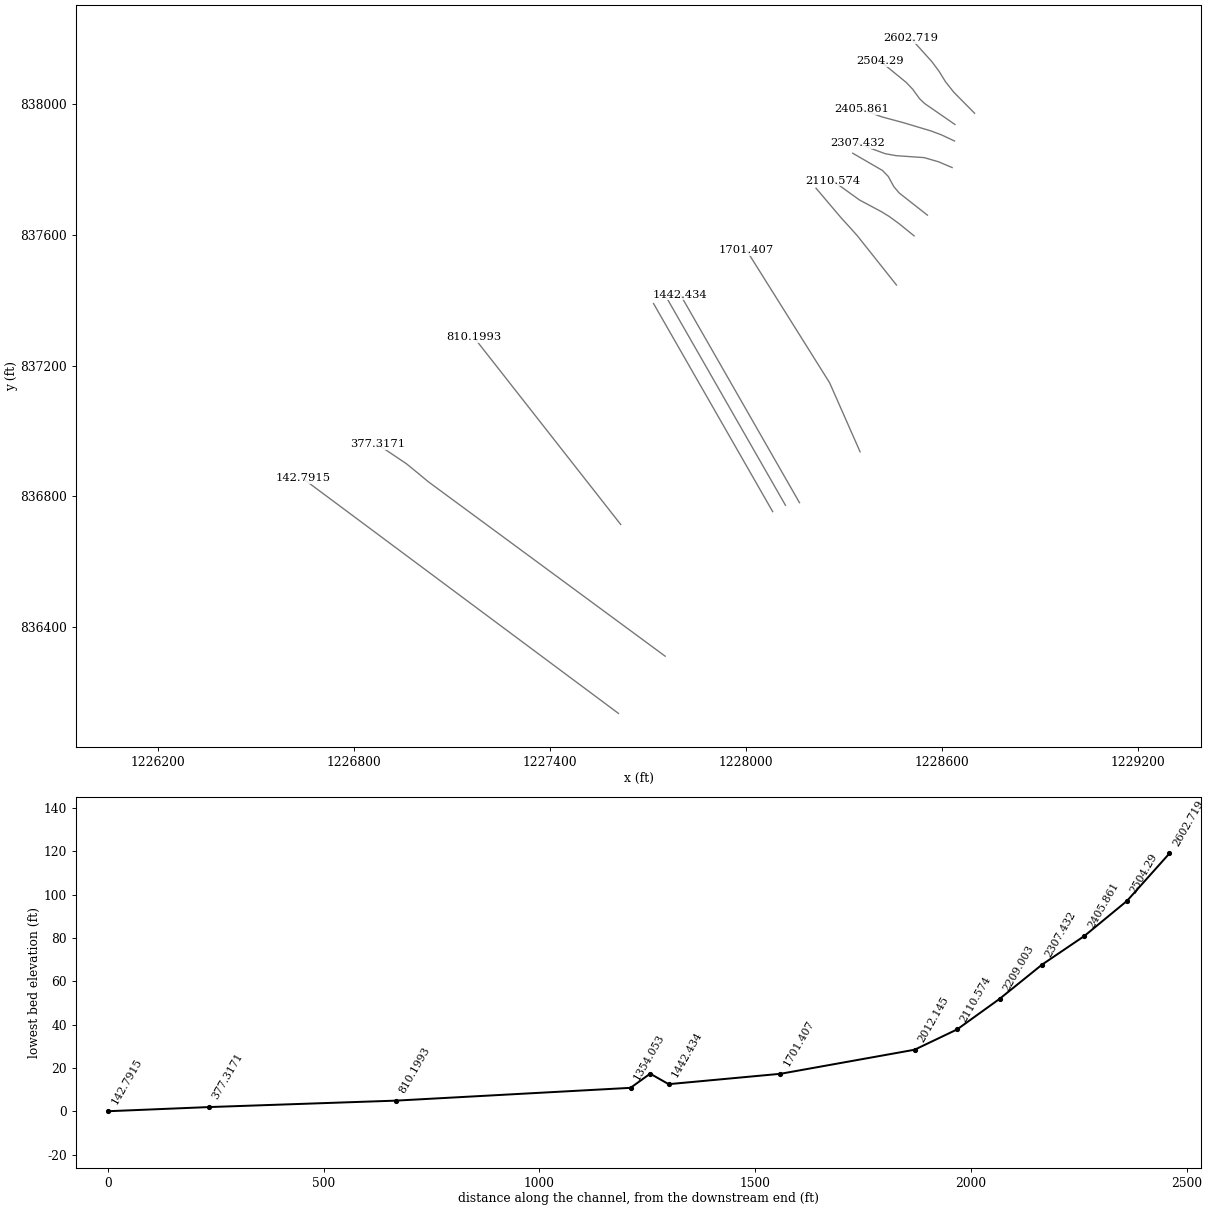
HEC-RAS study 5_ras.prj: 5

--- 5_ras.g01 (geometry) --- (continued)

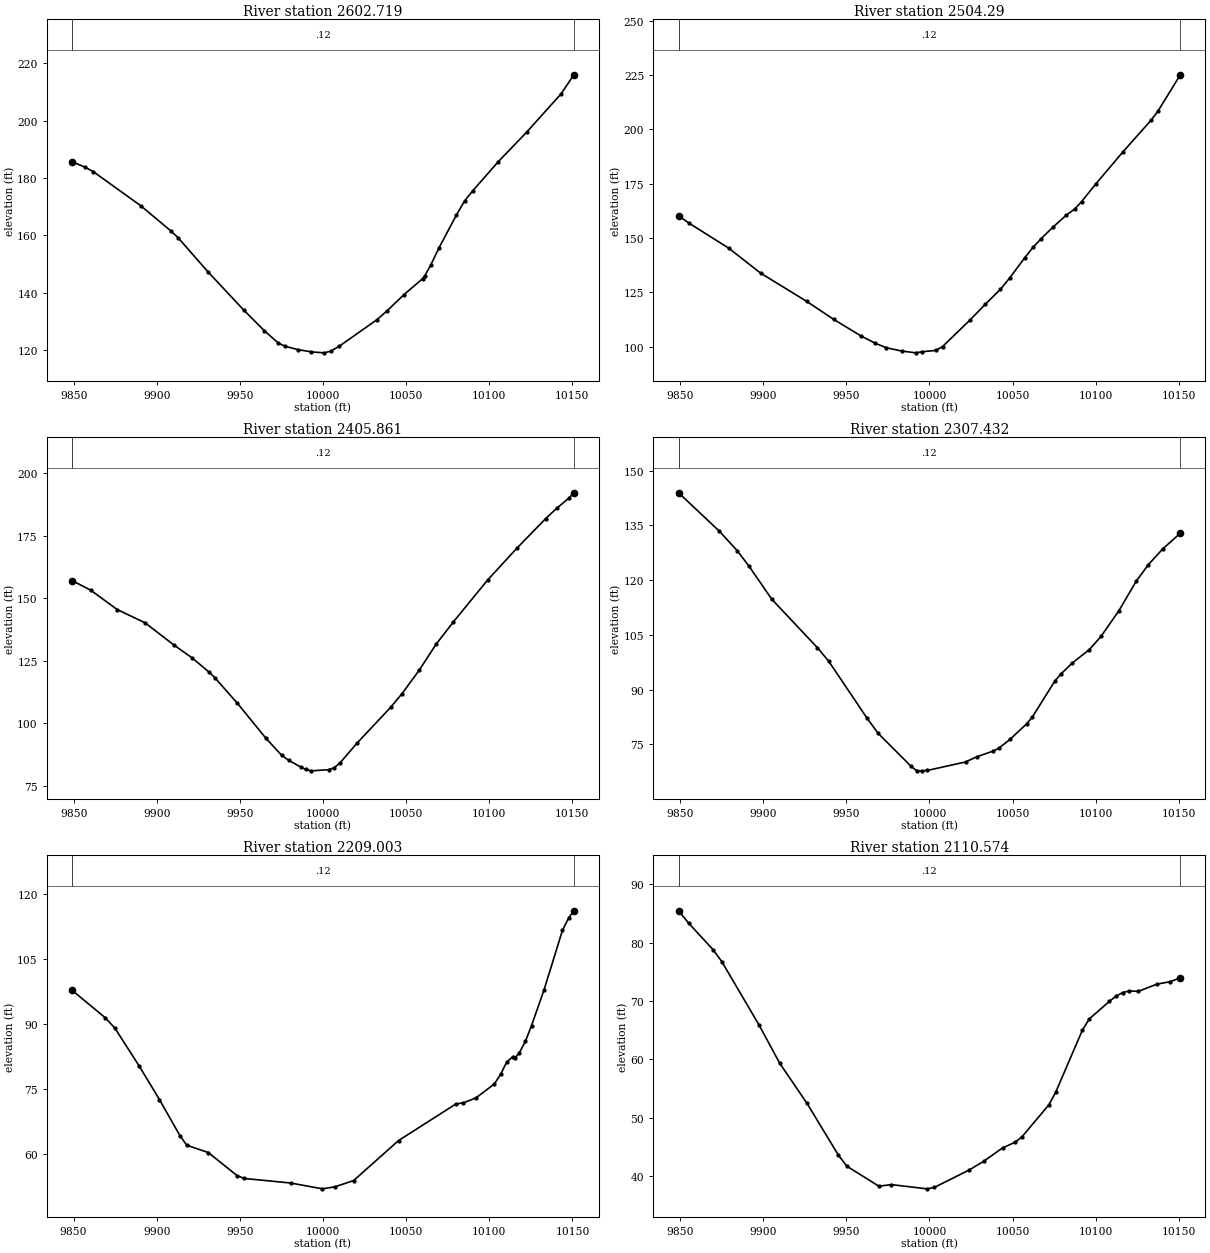
Type RM Length L Ch R = 1 ,2602.719,98.429000,98.429000,98.429000
XS GIS Cut Line= 6
1228698.74421902837972.5646381551228635.02665571838036.972306212
1228609.96101146838068.6770658631228589.94527377838101.043859931
1228568.02090387838130.5096190211228503.70268211838201.817711311
#Sta/Elev= 30
9849.043185.70259856.805183.79769861.861182.21499890.232170.42049908.357161.6472
9912.829159.2193 9930.72147.38489952.214134.08969964.761126.79059973.125122.5132
9977.308121.36689984.874120.23469993.045119.436110000.73   119.110004.57 119.673
10009.86 121.42510032.34130.581510038.38133.6308 10048.7139.350410059.93144.9331
10061.29145.975710064.98 149.82810069.92155.795710080.16166.955610085.21172.0272
10090.27175.664710105.43185.676710122.54195.974310143.34209.382710150.97215.9864
#Mann= 3 , 0 , 0
9849.043    0.12       09849.043    0.12       010150.97    0.12       0
#XS Ineff= 2 , 0
       0                               0
Bank Sta=9849.043,10150.97
Exp/Cntr=0.3,0.1

Type RM Length L Ch R = 1 , 2504.29,98.429000,98.429000,98.429000
XS GIS Cut Line= 6
1228638.68704256837938.1725355891228545.63105407 838002.47225885
1228530.34740209 838017.156901741228509.14501663838046.271036889
1228489.57815557838066.8665183311228409.73467691838132.118245288
#Sta/Elev= 30
 9849.05160.25839855.091156.95939879.323145.28149898.427133.83899926.165120.8332
9942.485112.51089958.806104.94159967.515101.53299974.07799.517939983.38897.98106
9991.76697.161639995.736 97.687710003.8198.2668210007.87100.0217 10024.4 112.243
 10033.7119.563810042.76 126.41510048.18131.500610057.25140.805210062.26145.6335
10067.28149.736410074.22154.931310082.31160.469410087.33163.278110091.58166.7654
10099.93174.710910116.59189.765810133.25204.095710137.42208.270310150.96225.0956
#Mann= 3 , 0 , 0
 9849.05    0.12       0 9849.05    0.12       010150.96    0.12       0
#XS Ineff= 2 , 0
       0                               0
Bank Sta=9849.05,10150.96
Exp/Cntr=0.3,0.1

Type RM Length L Ch R = 1 ,2405.861,98.429000,98.429000,98.429000
XS GIS Cut Line= 6
1228637.37516886 837887.659384541228596.71714544837906.645605554
1228565.52719725837918.3490741551228482.48392182837943.244759355
1228413.63476094837961.8781842771228352.04200855837984.799511417
#Sta/Elev= 30
9849.029157.00749860.375153.10489876.204145.42569892.964140.13119910.515131.1571
9921.028126.24179931.439120.46759934.861118.27239948.551107.96149965.66294.02209
9975.06887.267249979.35185.209939986.59882.561629989.61881.560089993.04181.01411
10003.3481.4703810006.7782.2659910010.2184.1396610020.4592.0425810040.84106.4755
10047.64 111.89210057.83121.149710068.03 131.53510078.23140.297510099.02157.1814
10116.52169.815210134.03181.774610140.57185.830510148.03189.965210150.96192.0615
#Mann= 3 , 0 , 0
9849.029    0.12       09849.029    0.12       010150.96    0.12       0
#XS Ineff= 2 , 0
       0                               0
Bank Sta=9849.029,10150.96
Exp/Cntr=0.3,0.1

Type RM Length L Ch R = 1 ,2307.432,98.429100,98.429100,98.429100
XS GIS Cut Line= 6
1228629.97607227837806.3953230231228588.58456045837823.956145342
1228544.70720363837836.7412360241228458.71284178837842.769595558
1228425.11689241837848.8134402351228340.14128706837880.153163813
#Sta/Elev= 30
9849.096143.94759873.609133.44299884.301 128.1239891.429123.87429905.206114.7499
9932.544101.52519939.37997.806829962.59682.091129969.22777.974999988.98468.96857
9992.26667.772849995.54767.733349998.82867.85156 10021.870.17135 10028.471.57918
 10038.473.1537610041.7373.92951 10048.476.33601 10058.480.5817310061.7882.39826
10075.5492.4083910078.9894.2282410085.8697.2624710096.18100.948110103.25104.6064
10113.87111.550510124.49119.772710131.57124.181210140.38128.587110150.92132.8653
#Mann= 3 , 0 , 0
9849.096    0.12       09849.096    0.12       010150.92    0.12       0
#XS Ineff= 2 , 0
       0                               0
Bank Sta=9849.096,10150.92
Exp/Cntr=0.3,0.1

Type RM Length L Ch R = 1 ,2209.003,98.429000,98.429000,98.429000
XS GIS Cut Line= 6
1228554.43251729 837660.698451591228468.00788259837728.534740521
1228451.37680534837748.3463759271228434.66745635837779.060483088
1228416.86115687837797.4556711031228325.79449989837850.248151198
#Sta/Elev= 30
 9849.0997.820979868.93391.510199874.82789.080629889.37980.362649901.64772.54778
9913.91464.241329918.01862.00399 9930.9860.314749948.26254.989689952.58354.31665
9980.46353.267919999.643  51.91510007.0952.3778410018.3853.8220110045.4663.08628
10079.8371.5209510084.4571.8131410091.8972.9257710103.0676.1613710106.7978.38872
10110.51 81.253910114.2382.49239 10115.582.2327810117.9583.2785810121.6885.99495
 10125.489.6689410132.8597.8299710144.01111.704310147.74114.569510150.85 116.204
#Mann= 3 , 0 , 0
 9849.09    0.12       0 9849.09    0.12       010150.85    0.12       0
#XS Ineff= 2 , 0
       0                               0
Bank Sta=9849.09,10150.85
Exp/Cntr=0.3,0.1

Type RM Length L Ch R = 1 ,2110.574,98.429000,98.429000,98.429000
XS GIS Cut Line= 6
1228513.72483297837597.2937173821228466.95041009 837635.17911642
1228436.61719204837657.2398913921228413.41725288837671.457820347
1228346.48130984837707.1562042181228264.42440473837766.285707051
#Sta/Elev= 30
9849.02285.458619855.122 83.33299869.91578.758119875.12876.714899897.34265.94616
9909.97759.293989926.20452.514289945.25343.570229950.34841.679989969.58738.26153
9977.13838.534069998.53637.8102610002.9438.0547110023.7841.01809 10032.642.52348
   1004444.8237110051.7245.8180910055.7646.7535510071.9452.2274910075.9854.36768
10092.0465.00726 10096.266.9384510108.3469.9421710112.3870.8678910116.4271.45081
 10120.171.7101610125.7171.6583110136.9372.8876310144.73 73.300110150.97 73.9598
#Mann= 3 , 0 , 0
9849.022    0.12       09849.022    0.12       010150.97    0.12       0
#XS Ineff= 2 , 0
       0                               0
Bank Sta=9849.022,10150.97
Exp/Cntr=0.3,0.1

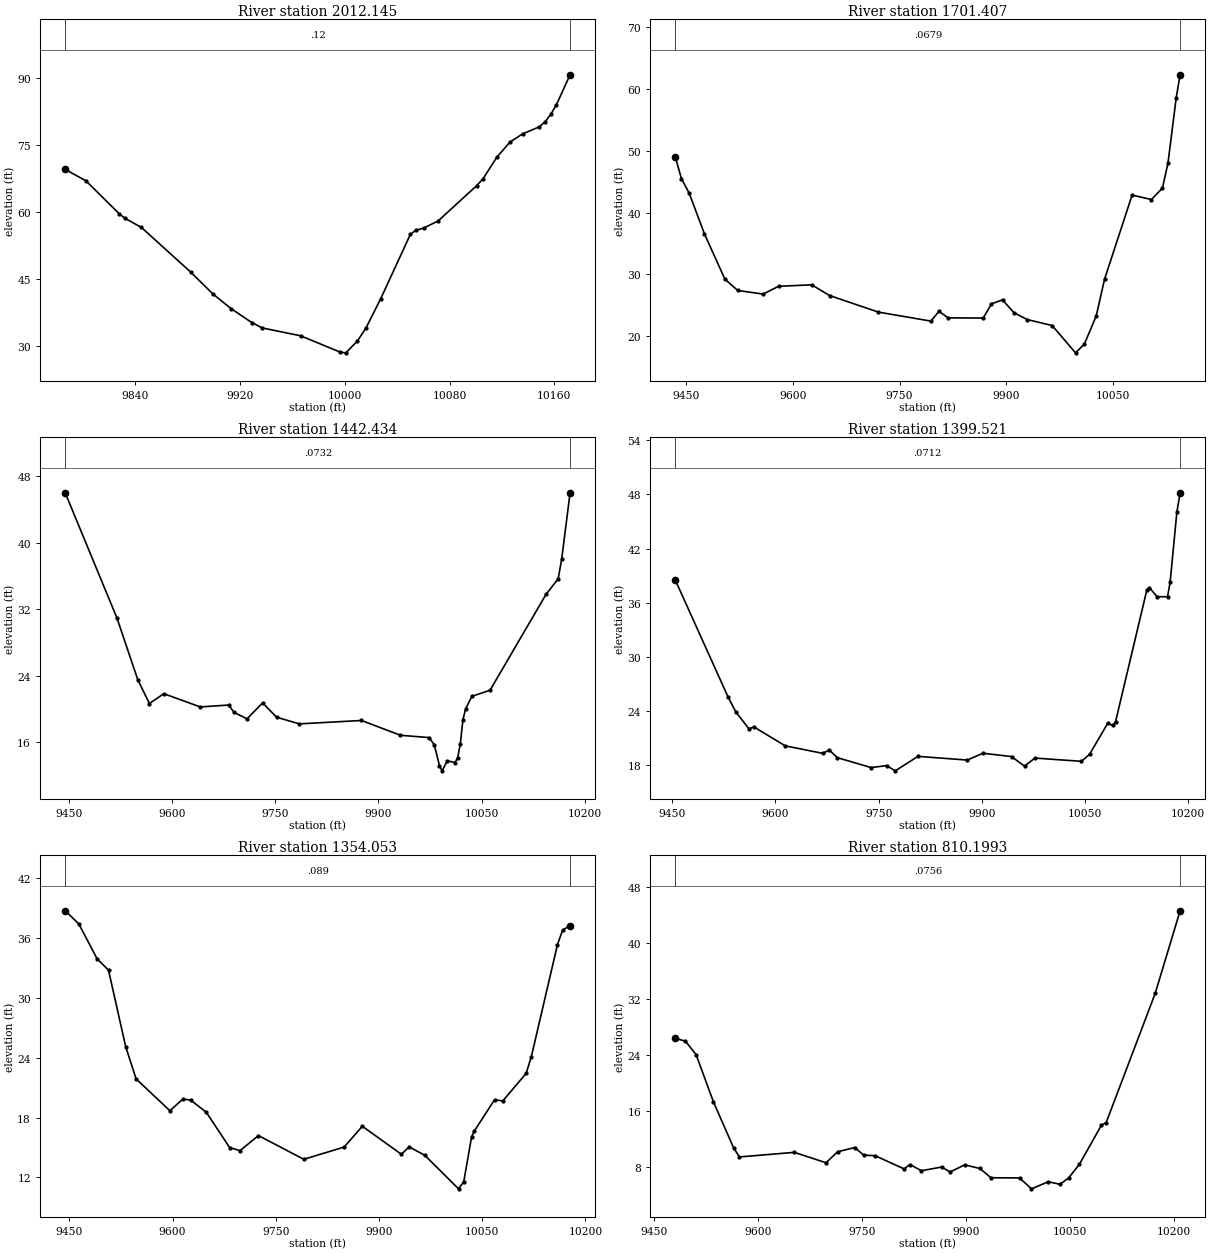
Type RM Length L Ch R = 1 ,2012.145,310.738200,310.738200,310.738200
XS GIS Cut Line= 6
1228459.71863944837446.8869367211228339.92589967837597.632683551
1228315.43630701837625.1430096991228314.05535556 837626.58972083
1228291.39855885837651.2516729491228213.57411932837743.119719614
#Sta/Elev= 30
9786.73269.492629802.46766.94787 9828.0259.53119 9832.21 58.56319844.78256.51785
9882.49846.49453 9899.2641.652069913.20838.349799929.02835.226589936.97634.02221
 9966.3132.260459996.432 28.614310000.8228.4452110009.6131.0741510016.1433.96731
10027.3740.5070810050.0554.9349110054.0255.8413910060.1356.3650410071.2257.94774
10100.7365.8792210105.6167.4208810115.96 72.182910126.1175.6092510135.7177.44185
10148.6179.0486510152.9180.1512710157.2181.8004310161.5183.94103   10172 90.6809
#Mann= 3 , 0 , 0
9786.732    0.12       09786.732    0.12       0   10172    0.12       0
#XS Ineff= 2 , 0
       09934.503                       0
Bank Sta=9786.732,10172
Exp/Cntr=0.3,0.1

Type RM Length L Ch R = 1 ,1701.407,258.972600,258.972600,258.972600
XS GIS Cut Line= 3
1228348.34050191836936.6123998321228255.09686765837147.766913721
1228001.19061765837552.714830388
#Sta/Elev= 30
9435.11248.947619443.66345.469599454.42343.167359475.94136.562279504.63329.25045
9522.56627.42169 9558.4326.832189579.94928.087699626.57428.325759651.67926.59543
9720.24623.917829793.821 22.46569805.43924.055229817.95922.989869867.39722.95571
9879.01425.259039894.504 25.89249910.59923.824089929.12722.720079964.20821.75192
9997.06317.3365610009.4218.7469610026.1723.3134610037.7829.2310810076.5142.83465
10103.6142.11178 10119.143.9556710126.85 47.992210138.4758.58649 10143.962.26925
#Mann= 3 , 0 , 0
9435.112  0.0679       09435.112  0.0679       0 10143.9  0.0679       0
#XS Ineff= 2 , 0
       09940.277                       0
Bank Sta=9435.112,10143.9
Exp/Cntr=0.3,0.1

Type RM Length L Ch R = 1 ,1442.434,42.913000,42.913000,42.913000
XS GIS Cut Line= 2
1228162.88043247836780.8398303881227798.29709914837417.558580388
#Sta/Elev= 30
9444.98945.954739520.087 30.92059550.33223.505349567.18420.644999588.13821.82824
9641.066 20.23779682.65320.466769690.21419.575669709.11718.804389731.801  20.726
9752.05618.999229785.06918.199739875.46418.607359932.17316.82793 9973.7616.54949
9981.32115.680379988.88213.154929992.66312.5494810000.2213.7533610011.5713.54631
10015.3514.1501510019.1315.7863410022.91 18.660410026.6919.9684410035.9721.51429
10062.38 22.246810143.8933.7981210161.41 35.653510166.57 38.0569 10178.746.00014
#Mann= 3 , 0 , 0
9444.989  0.0732       09444.989  0.0732       0 10178.7  0.0732       0
#XS Ineff= 2 , 0
       0 9934.02        10028.81       0
Bank Sta=9444.989,10178.7
Exp/Cntr=0.3,0.1

Type RM Length L Ch R = 1 ,1399.521,45.468500,45.468500,45.468500
XS GIS Cut Line= 2
1228119.91168247836773.0273303881227755.32834914837409.746080388
#Sta/Elev= 30
9454.53338.496799531.07225.575359542.41323.913429561.31722.052539568.87822.24306
9614.24520.153429668.52419.329189678.51519.685989689.85718.851529739.00517.74962
9761.68917.968319774.16517.388419807.17718.990719878.88818.582559901.571 19.3379
9943.15818.967959962.06117.904379977.18318.8033410044.8718.4413910056.5819.21488
10083.0422.65272 10090.622.4190510094.3822.8189810139.7537.3666310143.5337.68218
10154.8736.6654310169.9936.6673310173.7738.2957910183.5246.0246510188.2448.17811
#Mann= 3 , 0 , 0
9454.533  0.0712       09454.533  0.0712       010188.24  0.0712       0
#XS Ineff= 2 , 0
       09909.805        10030.77       0
Bank Sta=9454.533,10188.24
Exp/Cntr=0.3,0.1

Type RM Length L Ch R = 1 ,1354.053,543.853600,543.853600,543.853600
XS GIS Cut Line= 2
1228080.84918247836753.4960803881227716.26584914837390.214830388
#Sta/Elev= 30
9444.11438.737269463.76737.413089490.23133.923169506.865 32.78029531.818 25.1195
 9546.9421.879529596.08818.686649614.99119.859649626.33319.749519649.01718.53238
9683.04214.981849698.16514.68627 9724.7516.193939790.77513.816119849.38915.04262
9875.85317.128769932.56214.321529943.90415.063099966.58814.2180610015.7410.85289
 10023.311.5754810034.64 16.061610038.4216.6281910068.0819.7875210080.0119.66647
10114.0322.4408610121.5924.12116 10159.435.3180310166.9636.7972410177.8337.25271
#Mann= 3 , 0 , 0
9444.114   0.089       09444.114   0.089       010177.83   0.089       0
#XS Ineff= 2 , 0
       09876.605        10041.13       0
Bank Sta=9444.114,10177.83
Exp/Cntr=0.3,0.1

Type RM Length L Ch R = 1 ,810.1993,432.882200,432.882200,432.882200
XS GIS Cut Line= 2
1227615.77395099836714.1731637211227165.88245793837287.639598907
#Sta/Elev= 30
9480.37726.373829494.98825.973729510.33424.052779535.35417.338399564.54310.76326
9572.8839.4889249652.113 10.14029697.9828.6597059714.66210.220969739.495 10.8312
9752.1929.7520859768.8729.6624979810.5717.7884699819.2258.4042569835.5917.524257
9864.7818.0448269877.2917.355346 9898.148.3613379920.217 7.841369936.163 6.52318
 9977.376.4982569994.6324.94410510019.075.95958110035.755.58577510048.266.498798
10063.738.42167910095.6214.0059110102.4714.3738110173.3632.7967210209.2644.54843
#Mann= 3 , 0 , 0
9480.377  0.0756       09480.377  0.0756       010209.26  0.0756       0
#XS Ineff= 2 , 0
       09643.276                       0
Bank Sta=9480.377,10209.26
Exp/Cntr=0.3,0.1

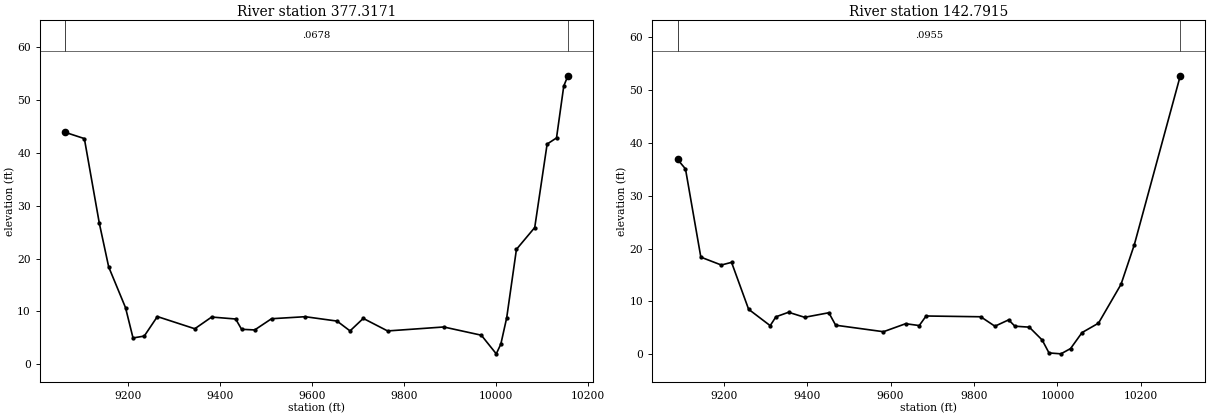
Type RM Length L Ch R = 1 ,377.3171,234.525600,234.525600,234.525600
XS GIS Cut Line= 6
1227751.81995793836311.0770989061227027.59491929836844.432387643
1226999.22533046836867.9171327221226997.71395233836869.226993843
1226960.24986927836899.8332156911226870.86677734836959.859957739
#Sta/Elev= 30
9062.74443.862279104.36842.680249136.96426.652149157.33718.402029194.00710.69768
9210.305 4.974819234.7535.3326339263.2749.0215529344.7656.7157989381.4358.930908
9433.6968.5599429446.6286.6125599475.1496.491253 9511.828.6126559585.1628.995511
9654.4288.1668669682.6666.3088819711.472  8.67399764.4416.3029169886.6767.051601
9968.4385.497922   100011.97175110010.973.81702710023.728.79609310044.9121.73328
10084.7325.8584610111.7241.6465710132.1542.8045410147.9652.6281210157.0554.55955
#Mann= 3 , 0 , 0
9062.744  0.0678       09062.744  0.0678       010157.05  0.0678       0
#XS Ineff= 2 , 0
       09709.578                       0
Bank Sta=9062.744,10157.05
Exp/Cntr=0.3,0.1

Type RM Length L Ch R = 1 ,142.7915,0.000000,0.000000,0.000000
XS GIS Cut Line= 2
1227608.82950654836136.0481637211226642.44495793 836855.34793224
#Sta/Elev= 30
 9089.6836.882069108.62535.096079145.43418.373169194.51316.879839219.05217.38447
9259.9518.4935279311.6535.3893529325.3897.0700069355.6117.9283089394.0746.974427
9452.1767.8348869468.5365.4744469583.0524.2411579636.2215.7578379668.8145.409244
9685.2997.2211349816.1767.0747719850.1425.2831469883.1116.4888599897.9745.288679
9932.5645.1039499963.4122.6696869979.7720.223381 10008.40.04885810031.471.048828
10058.944.07684510098.385.86127310152.3613.2160910184.2720.7357410294.3852.74276
#Mann= 3 , 0 , 0
 9089.68  0.0955       0 9089.68  0.0955       010294.38  0.0955       0
#XS Ineff= 2 , 0
       09912.225                       0
Bank Sta=9089.68,10294.38
Exp/Cntr=0.3,0.1